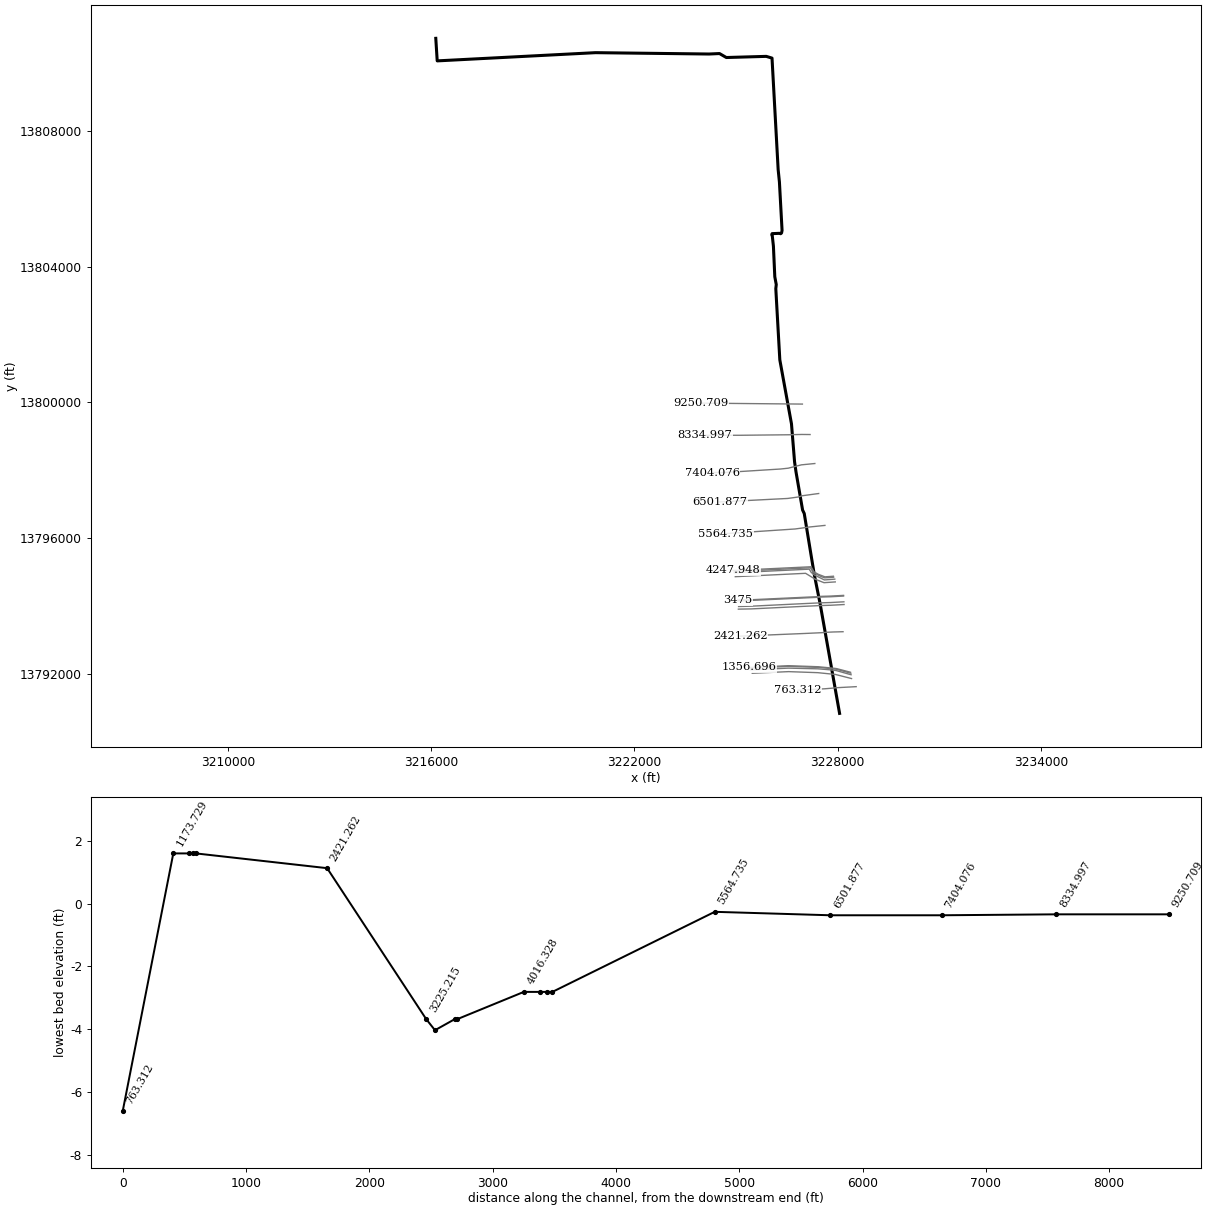
--- A104-07-00.prj (project) ---

Proj Title=A104-07-00
Current Plan=p02
Default Exp/Contr=.3,.1
English Units
Geom File=g01
Flow File=f01
Flow File=f02
Plan File=p01
Plan File=p02
Y Axis Title=Elevation
X Axis Title(PF)=Main Channel Distance
X Axis Title(XS)=Station
BEGIN DESCRIPTION:
Clear Creek Basin
Taylor Bayou Tributary 3.93
A104-07-00
Flood Hazard Model
10%, 2%, 1% and 0.2% Events
Filename: A104-07-00.prj
Prepared by: Perry Vaught	Date: 4-27-04
Reviewed by: __________	Date:
Status (FINAL)
TSARP Effective + LOMR 20-06-0975P effective on 04/03/2020
END DESCRIPTION:
DSS Export Rating Curves= 0
DSS Export Rating Curve Sorted= 0
DSS Export Volume Flow Curves= 0
DXF OffsetX= 0
DXF OffsetY= 0
DXF ScaleX= 1
DXF ScaleY= 10

--- A104-07-00.p02 (plan) ---

Plan Title=Effective Floodway 2020
Version=Version 3.0.1  May 2012
Short Identifier=Eff FW 2020
Geom File=g01
Flow File=f02
Subcritical Flow
K Sum by GR= 0
Std Step Tol= 0.01
Critical Tol= 0.01
Num of Std Step Trials= 20
Max Error Tol= 0.3
Flow Tol Ratio= 0.001
Split Flow NTrial= 30
Split Flow Tol= 0.02
Split Flow Ratio= 0.02
Log Output Level= 0
Friction Slope Method= 1
Unsteady Friction Slope Method= 2
Parabolic Critical Depth
Global Vel Dist= 0 , 0 , 0
Global Log Level= 0
CheckData=True
Encroach Param=-1 ,0,0, 2
Encroach River=A104-07-00
Encroach Reach=A104-07-00_0008
Encroach Node=9250.709
       1 4944.47 5053.64
Encroach Node=8334.997
       1 4946.36 5053.64
Encroach Node=7404.076
       1 4940.77 5059.23
Encroach Node=6501.877
       1 4944.02 5055.98
Encroach Node=5564.735
       1 4947.44 5052.56
Encroach Node=4247.948
       1 4865.62 5080.24
Encroach Node=4203.118
       1 4968.26 5031.74
Encroach Node=4144.764
       1 4968.26 5031.74
Encroach Node=4016.328
       1 4922.93 5074.05
Encroach Node=3475
       1 4949.34 5050.66
Encroach Node=3455.279
       1 4949.34 5050.66
Encroach Node=3295.833
       1 4949.34 5050.66
Encroach Node=3225.215
       1 4949.34 5050.66
Encroach Node=2421.262
       1 4946.86 5053.14
Encroach Node=1356.696
       1 4896.06 5054.17
Encroach Node=1336.02
       1    4934 5054.17
Encroach Node=1298.46
       1 4945.83 5054.17
Encroach Node=1173.729
       1    4936 5054.17
Encroach Node=763.312
       1 4955.42 5044.58
Computation Interval=1HOUR
Output Interval=1HOUR
Run HTab= 0
Run UNet= 0
Run PostProcess= 0
UNET Theta= 1
UNET ZTol= 0.02
UNET ZSATol= 0.1
UNET MxIter= 20
UNET MaxInSteps= 20
UNET DtIC= 0
UNET DtMin= 0
UNET MaxCRTS= 20
UNET WFStab= 2
UNET SFStab= 1
UNET WFX= 1
UNET SFX= 1
UNET Convert EG Bridges=-1
UNET Use Existing IB Tables=-1
Instantaneous Interval=1HOUR
DSS File=dss
Write IC File= 0
IC Time=0
Write Velocity= 0
Write Detailed= 0

--- A104-07-00.p01 (plan) ---

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Plan Title=Effective MP 2020
Short Identifier=Eff MP 2020
Geom File=g01
Flow File=f01
Std Step Tol= 0.003
Critical Tol= 0.003
Max Error Tol= 0.1
Secant Critical Depth
Encroach Param=-1 ,0,0, 0
BEGIN DESCRIPTION:
TSARP Effective + LOMR 20-06-0975P effective on 04/03/2020
END DESCRIPTION:

--- A104-07-00.f02 (steady flow) ---

Flow Title=Floodway
Version=Version 3.0.1  Mar 2001
Number of Profiles= 2
Profile Names= 1PCT_100yr,Floodway
River Rch & RM=A104-07-00,A104-07-00_0008 ,9250.709
    1043    1043
River Rch & RM=A104-07-00,A104-07-00_0008 ,8334.997
    1075    1075
River Rch & RM=A104-07-00,A104-07-00_0008 ,7404.076
    1107    1107
River Rch & RM=A104-07-00,A104-07-00_0008 ,6501.877
    1141    1141
River Rch & RM=A104-07-00,A104-07-00_0008 ,5564.735
    1191    1191
River Rch & RM=A104-07-00,A104-07-00_0008 ,4247.948
    1231    1231
River Rch & RM=A104-07-00,A104-07-00_0008 ,3225.215
    1263    1263
River Rch & RM=A104-07-00,A104-07-00_0008 ,2421.262
    1308    1308
River Rch & RM=A104-07-00,A104-07-00_0008 ,1356.696
    1333    1333
Boundary for River Rch & Prof#=A104-07-00,A104-07-00_0008 , 1
Up Type= 0
Dn Type= 3
Dn Slope=.0007
DSS Import GetInterval= 0
DSS Import GetPeak= 0
DSS Import FillOption= 0

--- A104-07-00.f01 (steady flow) ---

Flow Title=FEMA Effective June 2007
Version=Version 3.0.1  Mar 2001
Number of Profiles= 4
Profile Names=10PCT_10yr, 2PCT_50yr, 1PCT_100yr, 0.2PCT_500yr
River Rch & RM=A104-07-00,A104-07-00_0008      ,9250.709
     569     879    1043    1529
River Rch & RM=A104-07-00,A104-07-00_0008      ,8334.997
     587     906    1075    1576
River Rch & RM=A104-07-00,A104-07-00_0008      ,7404.076
     604     933    1107    1623
River Rch & RM=A104-07-00,A104-07-00_0008      ,6501.877
     623     962    1141    1673
River Rch & RM=A104-07-00,A104-07-00_0008      ,5564.735
     650    1004    1191    1746
River Rch & RM=A104-07-00,A104-07-00_0008      ,4247.948
     672    1038    1231    1805
River Rch & RM=A104-07-00,A104-07-00_0008      ,3225.215
     690    1065    1263    1853
River Rch & RM=A104-07-00,A104-07-00_0008      ,2421.262
     714    1103    1308    1918
River Rch & RM=A104-07-00,A104-07-00_0008      ,1356.696
     728    1124    1333    1955
Boundary for River Rch & Prof#=A104-07-00,A104-07-00_0008      , 1
Up Type= 0
Dn Type= 3
Dn Slope=.0007
DSS Import GetInterval= 0
DSS Import GetPeak= 0
DSS Import FillOption= 0

--- A104-07-00.g01 (geometry) ---

Geom Title=A104-07-00 2020
Version=Version 3.0.1  May 2012

River Reach=A104-07-00      ,A104-07-00_0008
Reach XY= 30
      3216139.25       13810721.      3216181.25       13810057.
      3220855.25       13810299.      3224205.75       13810259.
       3224514.5    13810273.001        3224716.       13810156.
        3225894.       13810190.     3226065.002    13810138.816
     3226246.173    13806855.561       3226283.5    13806489.001
       3226361.5       13805063.       3226346.5       13804988.
        3226320.       13804967.       3226280.5       13804978.
      3226067.75    13804969.001       3226056.5    13804937.001
       3226073.5    13804897.001      3226106.25    13804601.001
        3226147.       13803700.      3226190.25       13803468.
      3226176.75       13803348.      3226295.25       13801252.
       3226639.5       13799367.       3226730.5       13798250.
      3226773.75       13797948.      3226967.75       13796828.
       3227016.5       13796726.        3227309.       13794948.
      3227483.25       13794078.       3228059.5       13790840.

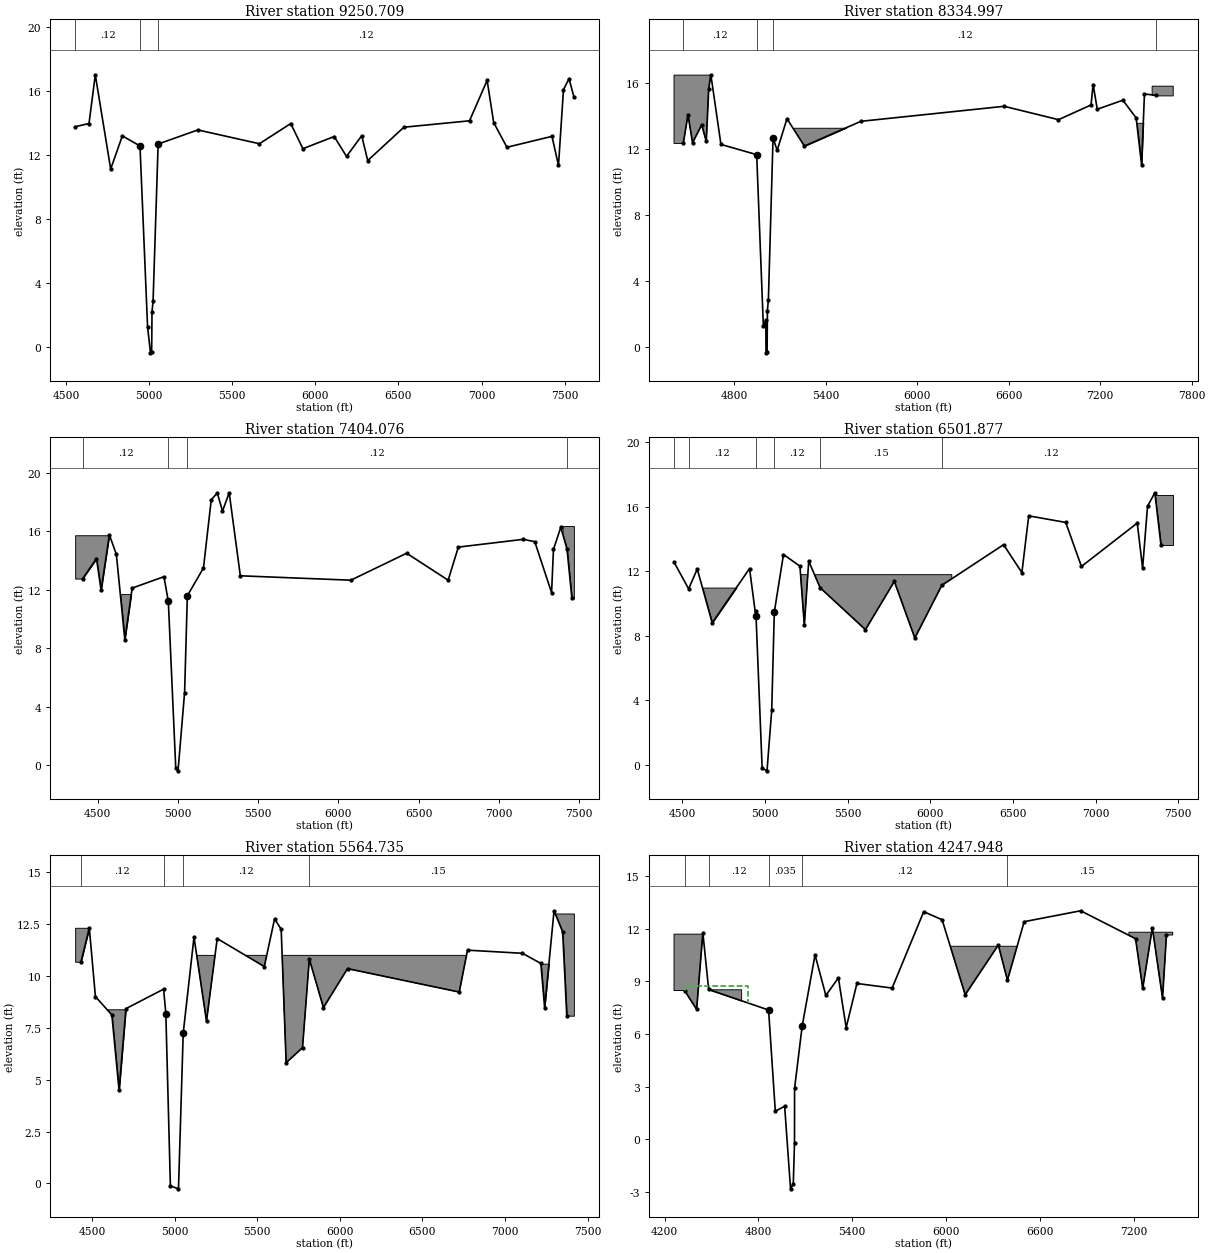
Type RM Length L Ch R = 1 ,9250.709,907.3,915.71,922.96
XS GIS Cut Line= 2
     3226961.945    13799949.208     3223960.433    13799977.147
#Sta/Elev= 30
 4554.26   13.76 4637.58   13.96 4675.43      17 4767.99   11.12 4838.28   13.19
 4944.47   12.56 4990.04    1.29 5007.51    -.34 5014.64     -.3 5016.78    2.22
 5023.17    2.89 5053.64   12.68 5292.53   13.56 5663.32    12.7 5851.85   13.96
 5924.81   12.39 6113.23   13.15 6187.45   11.91 6278.97    13.2 6315.08   11.65
  6532.8   13.73 6927.83   14.13 7033.82   16.65 7073.27   14.02 7152.94   12.48
  7424.1   13.16 7463.28   11.35 7493.29   16.07 7526.67   16.76  7555.9   15.63
#Mann= 3 ,-1 , 0
 4554.26     .12       0 4944.47    .035       0 5053.64     .12       0
Bank Sta=4944.47,5053.64
XS Rating Curve= 0
Exp/Cntr=.3,.1

Type RM Length L Ch R = 1 ,8334.997,895.76,930.92,1009.99
XS GIS Cut Line= 6
     3227188.818    13799052.215     3226938.115     13799054.42
     3226707.233    13799049.846     3226600.026    13799045.907
     3225103.535     13799030.27      3224086.83    13799029.756
#Sta/Elev= 30
 4464.87   12.35 4495.64   14.09 4525.64   12.39 4585.65   13.48 4615.65   12.47
 4631.62   15.66 4645.65   16.51 4711.83   12.29 4946.36   11.67 4990.04    1.29
 5006.25    1.66 5007.51    -.34 5014.64     -.3 5016.78    2.22 5023.17    2.89
 5053.64   12.68 5080.71   11.93  5145.1   13.85 5259.04   12.19 5629.92   13.69
 6569.88    14.6 6926.32   13.79 7139.97   14.68  7153.6   15.92 7180.85   14.42
  7348.6   14.97 7435.85    13.9 7471.62   11.06 7490.37   15.35 7567.07   15.26
#Mann= 4 ,-1 , 0
 4464.87     .12       0 4946.36    .035       0 5053.64     .12       0
 7567.07     .15       0
#Block Obstruct= 4 ,-1
  4403.9 4648.93   16.49 7537.54  7675.8   15.85    7430    7500    13.6
    5160    5570    13.3
Bank Sta=4946.36,5053.64
XS Rating Curve= 0
Exp/Cntr=.3,.1

Type RM Length L Ch R = 1 ,7404.076,904.01,902.2,881.72
XS GIS Cut Line= 6
     3227329.291    13798198.829     3226931.954     13798159.42
     3226542.853    13798061.178     3226315.466    13798036.824
     3224675.561     13797934.33     3224301.347    13797932.831
#Sta/Elev= 30
 4407.33   12.76 4493.28   14.12    4522   11.97 4573.52   15.75 4617.14   14.41
 4669.86    8.58 4715.32   12.11 4913.33   12.89 4940.77    11.2 4987.07    -.19
 5001.17    -.37 5042.06    4.98 5059.23   11.59 5159.49   13.48 5208.03   18.14
 5245.56   18.61 5278.04   17.37 5319.83   18.62 5389.27   12.95 6077.24   12.65
 6425.07   14.49 6683.61   12.65 6747.03   14.91 7151.25   15.44 7222.98   15.28
 7327.79    11.8 7339.51   14.75 7385.07   16.26 7424.02   14.77 7454.49    11.4
#Mann= 4 ,-1 , 0
 4407.33     .12       0 4940.77    .035       0 5059.23     .12       0
 7424.02     .15       0
#Block Obstruct= 3 ,-1
 4360.47  4574.1   15.72 7395.71 7466.63   16.35    4620    4720    11.7
Bank Sta=4940.77,5059.23
XS Rating Curve= 0
Exp/Cntr=.3,.1

Type RM Length L Ch R = 1 ,6501.877,947.46,937.14,918.79
XS GIS Cut Line= 5
     3227442.657    13797315.156     3226952.939    13797248.901
     3226846.666    13797213.694     3226527.067     13797169.91
     3224511.692    13797066.922
#Sta/Elev= 30
 4448.97   12.58 4537.37   10.92  4589.7   12.15 4680.03    8.81 4906.13   12.18
 4944.02    9.21 4944.02    9.56 4982.31    -.21 5011.73    -.37 5040.14    3.38
 5055.98    9.49  5111.4   13.05 5210.97   12.33  5237.6    8.68 5264.23   12.64
 5332.99   10.99 5607.33    8.39 5782.23   11.38  5906.2    7.87 6069.67   11.14
  6443.1   13.66 6554.02   11.93  6595.3   15.45 6819.31   15.04  6914.2   12.31
 7252.07      15 7284.48    12.2 7314.23   16.05 7358.56   16.88 7395.69   13.62
#Mann= 6 ,-1 , 0
 4448.97     .15       0 4537.37     .12       0 4944.02    .035       0
 5055.98     .12       0 5332.99     .15       0 6069.67     .12       0
#Block Obstruct= 3 ,-1
 7353.99 7466.63   16.72    5190    6130    11.8    4585    4900      11
Bank Sta=4944.02,5055.98
XS Rating Curve= 0
Exp/Cntr=.3,.1

Type RM Length L Ch R = 1 ,5564.735,1502.8,1316.79,1136.51
XS GIS Cut Line= 5
     3227627.132    13796376.011     3227116.375    13796323.325
     3227012.588    13796306.684     3226745.928    13796270.755
     3224698.668    13796134.222
#Sta/Elev= 30
 4434.15   10.69 4484.32   12.32 4521.36    9.01 4620.81    8.13 4664.45    4.49
 4705.87    8.43 4933.86    9.37 4947.44    8.19 4975.04    -.12 5023.93    -.26
 5052.56    7.25 5117.85   11.88 5193.53    7.83 5258.28   11.81 5543.27   10.46
 5605.45   12.76  5645.4   12.26 5675.46    5.82 5774.57    6.55  5815.7   10.82
 5901.16    8.48 6046.87   10.36    6723    9.23  6772.9   11.25 7105.29    11.1
 7216.77   10.61 7239.63    8.47 7296.66   13.15 7348.74   12.13 7373.61    8.09
#Mann= 4 ,-1 , 0
 4434.15     .12       0 4933.86    .035       0 5052.56     .12       0
  5815.7     .15       0
#Block Obstruct= 5 ,-1
 4398.75 4483.35   12.33    7190    7275    10.6 7299.76 7416.57   13.02
    5120    6772      11    4550    4760     8.4
Bank Sta=4947.44,5052.56
XS Rating Curve= 0
Exp/Cntr=.3,.1

Type RM Length L Ch R = 1 ,4247.948,35.06,44.83,30.14
XS GIS Cut Line= 6
     3227876.999    13794879.396     3227626.962     13794861.39
     3227427.079     13794937.85     3227302.473    13795009.708
     3227218.068    13795158.133     3224918.213    13795048.227
#Sta/Elev= 30
 4328.13    8.48 4405.36    7.41 4445.27   11.76 4482.23    8.54 4865.62    7.37
 4908.49    1.61 4968.26    1.89 5005.94   -2.81 5023.56   -2.51 5031.33    -.18
 5031.74    2.91 5080.24    6.45  5162.6   10.51  5231.7     8.2 5311.93     9.2
 5361.72    6.37 5430.49    8.88 5655.61    8.62 5857.64   12.97 5975.16   12.51
 6122.97    8.24 6334.71   11.07 6393.04    9.07 6500.03    12.4 6861.26   13.02
 7212.44   11.43 7258.16     8.6 7319.78   12.05 7384.92    8.05 7410.09   11.64
#Mann= 5 ,-1 , 0
 4328.13     .07       0 4482.23     .12       0 4865.62    .035       0
 5080.24     .12       0 6393.04     .15       0
#XS Ineff= 2 , 0
       0    4736    8.75    5155       0      10
Permanent Ineff=
       F       F
#Block Obstruct= 4 ,-1
 4260.68 4446.33   11.69    7170    7450    11.8    6020    7170      11
    4477    4690    8.55
Bank Sta=4865.62,5080.24
XS Rating Curve= 0
Exp/Cntr=.5,.3

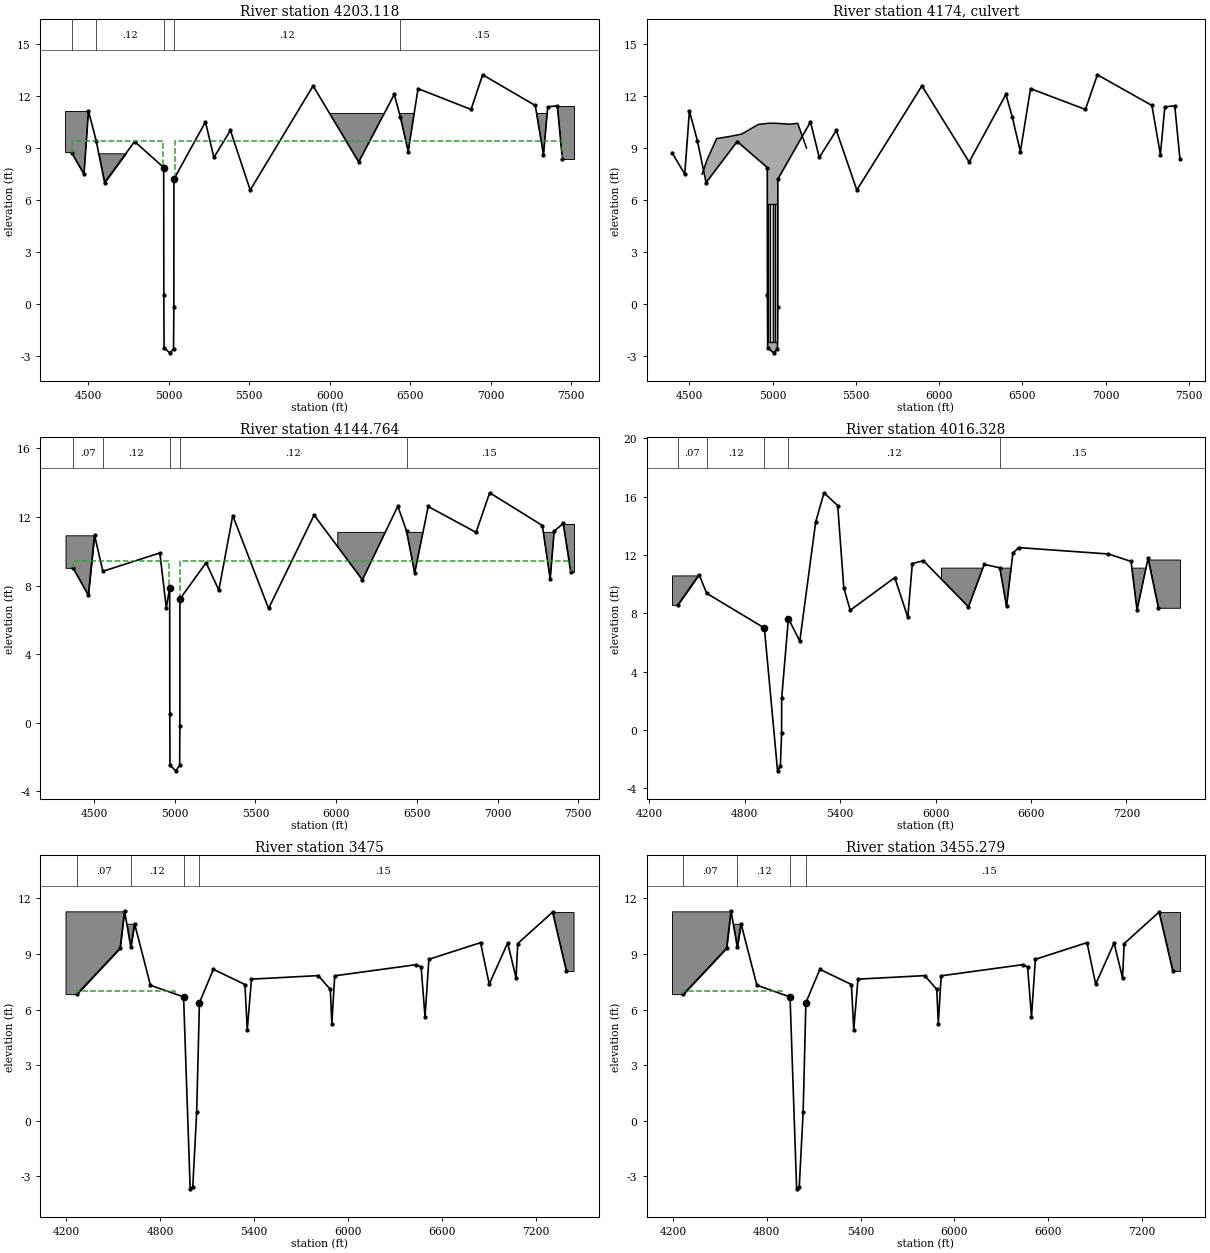
Type RM Length L Ch R = 1 ,4203.118,63.07,58.35,38.44
XS GIS Cut Line= 6
     3227883.586    13794849.792      3227622.83    13794831.015
     3227520.568    13794867.453     3227282.927    13794986.165
     3227199.679     13795127.22     3224952.387    13795019.826
#Sta/Elev= 30
4395.889    8.744472.629     7.5 4500.68   11.144548.439    9.43 4600.68    7.01
  4787.5    9.38 4968.26    7.88    4969     .53 4970.69   -2.525005.939   -2.81
 5029.44    -2.6 5031.33    -.185031.741    7.215227.719   10.51 5280.35    8.46
 5383.01   10.02 5506.05    6.58 5896.99   12.596180.539     8.2 6401.52    12.1
  6440.1   10.77 6488.28     8.8 6549.33   12.43 6878.97   11.23 6950.87   13.23
7278.101   11.46 7329.24    8.62 7355.68   11.38 7415.33   11.44 7446.95    8.35
#Mann= 5 ,-1 , 0
4395.889     .07       04548.439     .12       0 4968.26    .035       0
5031.741     .12       0  6440.1     .15       0
#XS Ineff= 2 , 0
       04963.989    9.43 5036.33       0    9.43
Permanent Ineff=
       F       F
#Block Obstruct= 4 ,-1
  4357.8 4502.46   11.11 4502.46    4770     8.7 7405.16 7516.09   11.44
    5980    7378      11
Bank Sta=4968.26,5031.741
XS Rating Curve= 0
Exp/Cntr=.5,.3

Type RM Length L Ch R = 2 ,4174    ,,,
BEGIN DESCRIPTION:
RAILROAD BRIDGE
END DESCRIPTION:
Bridge Culvert--1,0,-1,-1, 0
Deck Dist Width WeirC Skew NumUp NumDn MinLoCord MaxHiCord MaxSubmerge Is_Ogee
10,35,2.6,0, 11, 11, , , .95, 0, 0,0,,
    4577    4605    4664    4741    48154914.919    4984 5044.11 5101.675151.041
    5204
     7.5    8.29    9.55    9.67    9.81   10.37   10.44   10.42   10.38   10.43
       9
                                                                                
        
    4577    4605    4664    4741    48154914.919    4984 5044.11 5101.675151.041
    5204
     7.5    8.29    9.55    9.67    9.81   10.37   10.44   10.42   10.38   10.43
       9
                                                                                
        
BR Coef=-1 , 0 , 0 ,, 0 ,,,.8,-1,,0,
WSPro=,,,, 1 ,,,, 0 ,,,, 0 ,,,,-1 ,-1 ,-1 , 0 , 0 , 0 , 0 , 0
Multiple Barrel Culv=2,8,14,35,.012,.5,1,10,1,-2.2,-2.3, 4,Culvert #1  , 0 ,10
 4978.25 4978.25 4992.75 4992.75 5007.25 5007.25 5021.75 5021.75
Culvert Bottom n=.012
BC Design=,, 0 ,, 0 ,,,,,,

Type RM Length L Ch R = 1 ,4144.764,80.77,128.44,117.5
XS GIS Cut Line= 6
     3227917.895    13794793.335     3227611.076    13794769.893
     3227317.221    13794915.645     3227223.187    13794990.872
     3227163.241    13795087.256     3224952.161     13794981.17
#Sta/Elev= 30
 4369.12    9.03 4463.95    7.444502.439   10.95 4554.22    8.83 4907.28     9.9
 4947.29     6.7 4968.26    7.88    4969     .534970.149   -2.485005.939   -2.81
5030.181   -2.49 5031.33    -.185031.741    7.21 5193.82    9.33 5273.14    7.73
 5359.12   12.08 5581.18    6.665863.429   12.11 6162.64    8.33 6382.06   12.63
6436.069   11.19 6486.75    8.73 6570.44   12.616867.121    11.16951.291   13.41
7278.069    11.57326.479    8.38  7351.2   11.17 7407.09   11.62 7454.13    8.76
#Mann= 5 ,-1 , 0
 4369.12     .07       0 4554.22     .12       0 4968.26    .035       0
5031.741     .12       06436.069     .15       0
#XS Ineff= 2 , 0
       04964.431    9.43 5034.08       0    9.43
Permanent Ineff=
       F       F
#Block Obstruct= 3 ,-1
 4322.67 4502.43   10.936009.999    7380    11.17399.2217471.221   11.59
Bank Sta=4968.26,5031.741
XS Rating Curve= 0
Exp/Cntr=.5,.3

Type RM Length L Ch R = 1 ,4016.328,427.42,541.05,722.97
XS GIS Cut Line= 5
     3227931.771    13794711.794     3227600.497    13794688.789
     3227340.729     13794791.05     3227056.277    13794965.012
     3224981.028    13794865.705
#Sta/Elev= 30
 4378.92    8.58 4512.24   10.65 4560.26    9.37 4922.93    6.99 5005.94   -2.81
 5023.56   -2.51 5031.33    -.18 5031.74    2.17 5074.05    7.64 5145.73    6.09
 5245.65   14.26 5298.03   16.27 5384.22   15.39  5422.4    9.75 5463.08    8.21
  5743.2   10.45 5825.15    7.73 5853.82   11.41 5923.09   11.61  6206.9    8.44
 6306.03   11.36 6403.86   11.12 6446.19    8.47 6486.23   12.13 6521.96   12.51
 7086.92   12.07  7229.6   11.56 7267.13    8.23 7336.69   11.77 7401.22    8.38
#Mann= 5 ,-1 , 0
 4378.92     .07       0 4560.26     .12       0 4922.93    .035       0
 5074.05     .12       0 6403.86     .15       0
#Block Obstruct= 4 ,-1
 4341.68 4513.86    10.6 4533.97 4717.52     7.8 7341.48 7537.54   11.69
    6037    7338    11.1
Bank Sta=4922.93,5074.05
XS Rating Curve= 0
Exp/Cntr=.3,.1

Type RM Length L Ch R = 1 ,3475    ,20,20,20
XS GIS Cut Line= 6
       3228175.9     13794315.32     3227787.359     13794294.23
     3227496.011     13794285.69     3227394.043     13794276.91
     3225449.479     13794186.87      3225054.11      13794176.4
#Sta/Elev= 30
 4267.95    6.83  4543.7    9.31 4571.73   11.33 4612.08    9.37 4635.93   10.64
 4737.38    7.31 4949.34    6.68 4991.54   -3.68 5008.16   -3.58 5033.22     .49
 5050.66    6.37 5139.95    8.17 5341.65    7.35 5356.55    4.91 5383.47    7.64
 5810.01    7.83 5887.42    7.09 5897.28    5.24 5915.61    7.82 6436.06    8.42
 6467.97     8.3    6493     5.6 6517.73    8.71 6847.88    9.61 6903.47    7.37
 7021.09    9.59 7075.03    7.71 7085.69    9.56 7308.69   11.26  7396.4    8.08
#Mann= 4 ,-1 , 0
 4267.95     .07       0 4612.08     .12       0 4949.34    .035       0
 5050.66     .15       0
#XS Ineff= 2 , 0
       0  4896.9    7.02 5126.34       0    7.84
Permanent Ineff=
       F       F
#Block Obstruct= 3 ,-1
 4194.49 4571.13    11.3  4578.6 4636.05   10.63 7309.23 7442.53   11.26
Bank Sta=4949.34,5050.66
XS Rating Curve= 0
Exp/Cntr=.5,.3

Type RM Length L Ch R = 1 ,3455.279,160.64,159.45,160.23
XS GIS Cut Line= 6
      3228176.98     13794295.35     3227788.242     13794274.24
     3227497.053     13794265.71     3227395.256     13794256.94
     3225450.226     13794166.88     3225054.639     13794156.41
#Sta/Elev= 30
 4267.95    6.83  4543.7    9.31 4571.73   11.33 4612.08    9.37 4635.93   10.64
 4737.38    7.31 4949.34    6.68 4991.54   -3.68 5008.16   -3.58 5033.22     .49
 5050.66    6.37 5139.95    8.17 5341.65    7.35 5356.55    4.91 5383.47    7.64
 5810.01    7.83 5887.42    7.09 5897.28    5.24 5915.61    7.82 6436.06    8.42
 6467.97     8.3    6493     5.6 6517.73    8.71 6847.88    9.61 6903.47    7.37
 7021.09    9.59 7075.03    7.71 7085.69    9.56 7308.69   11.26  7396.4    8.08
#Mann= 4 ,-1 , 0
 4267.95     .07       0 4612.08     .12       0 4949.34    .035       0
 5050.66     .15       0
#XS Ineff= 2 , 0
       0  4896.9    7.02 5126.34       0    7.84
Permanent Ineff=
       F       F
#Block Obstruct= 3 ,-1
 4194.49 4571.13    11.3  4578.6 4636.05   10.63 7309.23 7442.53   11.26
Bank Sta=4949.34,5050.66
XS Rating Curve= 0
Exp/Cntr=.5,.3

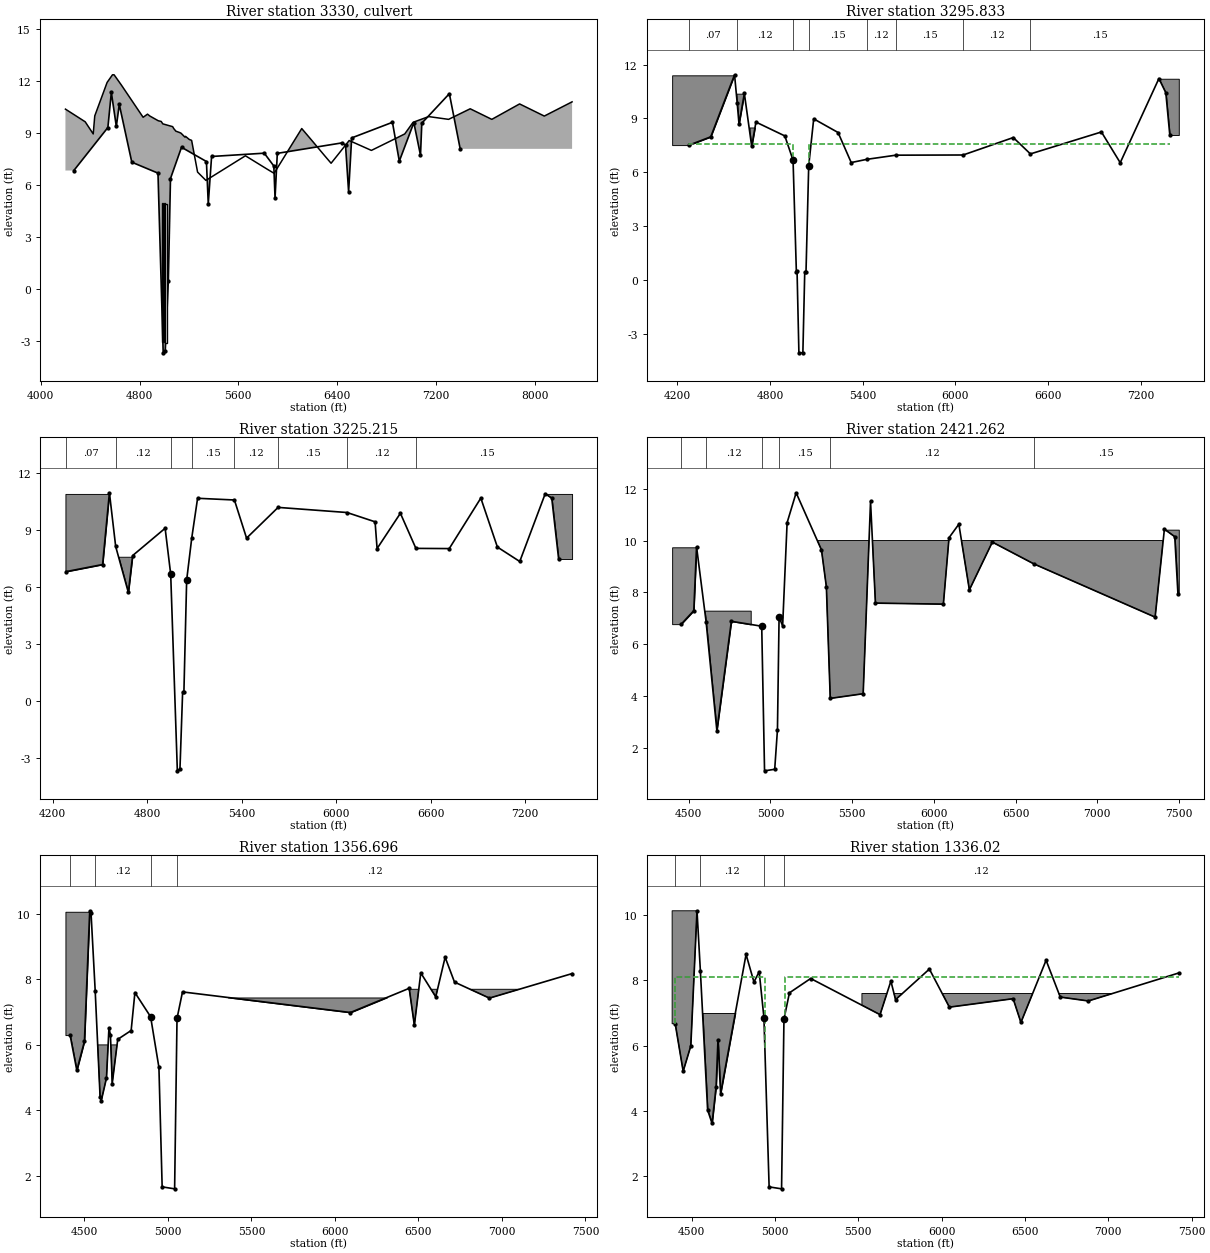
Type RM Length L Ch R = 2 ,3330    ,,,
BEGIN DESCRIPTION:
SHOREACRES BLVD. (updated from Isani Consultants Prop Plans on 01022015)
END DESCRIPTION:
Bridge Culvert--1,0,-1,-1, 0
Deck Dist Width WeirC Skew NumUp NumDn MinLoCord MaxHiCord MaxSubmerge Is_Ogee
52,83,2.6,0, 49, 48, , , .95, 0, 0,0,,
    4200    4360    4425 4437.44 4537.44 4581.01 4593.95 4652.76    4829  4864.6
 4883.97 4951.64  4975.2 4988.55 5068.21 5076.99 5094.17 5124.87 5136.47 5166.89
 5172.57 5202.97 5221.76 5269.94 5337.44 5404.94 5657.44 5835.44 5889.44 5943.44
 6033.44 6113.44 6193.44 6297.04 6351.04 6405.04 6497.44 6551.44 6677.44 6879.94
 6947.44 7014.94 7141.22 7302.44 7477.44 7652.44 7877.44 8077.44 8302.44
   10.37    9.64    8.94    9.98   11.91   12.35   12.35   11.76     9.9   10.08
    9.97     9.7    9.66    9.52    9.36    9.25     9.1    9.02    8.98    8.76
     8.8    8.62    8.57    6.74    6.26    6.56    7.68     6.9    6.67    7.29
    8.33    9.25    8.58     7.7    7.25    7.73    8.56    8.39    7.99     8.7
    8.94    9.61    9.94    9.78   10.39    9.78   10.67    9.97   10.79
                                                                                
                                                                                
                                                                                
                                                                                
                                                                        
    4200    4360    4425 4437.44 4537.44 4581.01 4593.95 4652.76    4829 4916.44
 4942.76 4994.04 5045.81 5075.41 5083.95 5095.83 5154.86 5207.73 5262.52 5266.82
 5270.11 5277.89 5280.87 5337.44 5404.94 5657.44 5835.44 5889.44 5943.44 6033.44
 6113.44 6193.44 6297.04 6351.04 6405.04 6497.44 6551.44 6677.44 6879.94 6947.44
 7014.94 7141.22 7302.44 7477.44 7652.44 7877.44 8077.44 8302.44
   10.37    9.64    8.94    9.98   11.91   12.35   12.35   11.76     9.9    9.45
    9.33    8.91    8.56    8.35    8.32    8.26    7.75    7.25    7.08    7.03
    7.14     6.8    7.13    6.26    6.56    7.68     6.9    6.67    7.29    8.33
    9.25    8.58     7.7    7.25    7.73    8.56    8.39    7.99     8.7    8.94
    9.61    9.94    9.78   10.39    9.78   10.67    9.97   10.79
                                                                                
                                                                                
                                                                                
                                                                                
                                                                
Culvert=2,8,10,117,.015,.5,1,8,3,-3.04,4988.37,-3.59,4987.16,Culvert #3  , 0 ,32
Culvert Bottom n=.015
Culvert=2,8,10,117,.015,.5,1,8,3,-3.05,5000,-3.43,5000,Culvert #2  , 0 ,32
Culvert Bottom n=.015
Culvert=2,8,10,117,.015,.5,1,8,3,-3.09,5013.65,-3.45,5011.92,Culvert #1  , 0 ,32
Culvert Bottom n=.015
BC Design=,, 0 ,, 0 ,,,,,,

Type RM Length L Ch R = 1 ,3295.833,70.74,70.62,70.37
XS GIS Cut Line= 6
     3228187.002    13794125.645     3227795.745    13794104.402
     3227505.248    13794095.848     3227031.078    13794073.945
     3225456.576    13793996.987     3225078.169    13793986.971
#Sta/Elev= 30
 4276.45    7.52 4416.44    7.98 4570.59   11.43 4587.66    9.86 4599.45    8.69
 4634.01   10.39 4681.65    7.45 4709.09     8.8 4896.11    8.03 4949.34    6.68
 4970.77     .47 4975.17     .52 4987.22   -4.03 5012.88   -4.02 5024.96     .45
 5033.22     .49 5050.66    6.37 5082.99    8.98 5240.73    8.22 5325.85    6.55
 5427.91    6.73 5614.64    6.96 6050.33    6.97 6375.22    7.94 6486.01    7.03
 6945.74    8.25  7067.5    6.54 7317.94   11.22 7362.75   10.43 7388.51    8.08
#Mann= 8 ,-1 , 0
 4276.45     .07       0 4587.66     .12       0 4949.34    .035       0
 5050.66     .15       0 5427.91     .12       0 5614.64     .15       0
 6050.33     .12       0 6486.01     .15       0
#XS Ineff= 2 , 0
       0 4949.34     7.6 5050.66       0     7.6
Permanent Ineff=
       F       F
#Block Obstruct= 4 ,-1
 4166.48 4569.37    11.4 4569.37 4634.14   10.38    4668    4705     8.5
 7317.86 7446.68   11.21
Bank Sta=4949.34,5050.66
XS Rating Curve= 0
Exp/Cntr=.5,.3

Type RM Length L Ch R = 1 ,3225.215,796.66,803.95,803.82
XS GIS Cut Line= 6
     3228192.255    13794045.812     3227799.275    13794024.475
     3227507.948    13794015.884     3227034.857    13793994.034
     3225459.565    13793917.038     3225071.218    13793909.948
#Sta/Elev= 30
 4287.68    6.82 4517.06    7.19 4560.37   10.97  4600.1    8.14 4680.55    5.72
 4707.63    7.66    4914     9.1 4949.34    6.68 4991.54   -3.68 5008.16   -3.58
 5024.96     .45 5033.22     .49 5050.66    6.37 5082.99    8.59    5120   10.68
 5353.77   10.59 5430.94    8.58 5631.09    10.2 6068.47    9.93 6246.73    9.44
 6259.38    8.03 6407.35    9.89 6505.86    8.04 6717.49    8.03 6917.94   10.69
 7023.07    8.11    7165    7.35 7326.63   10.92 7368.12   10.69 7411.88    7.48
#Mann= 8 ,-1 , 0
 4287.68     .07       0  4600.1     .12       0 4949.34    .035       0
 5082.99     .15       0 5353.77     .12       0 5631.09     .15       0
 6068.47     .12       0 6505.86     .15       0
#Block Obstruct= 3 ,-1
 4281.17 4560.58   10.91 7327.13 7497.18   10.91    4591    4878     7.6
Bank Sta=4949.34,5050.66
XS Rating Curve= 0
Exp/Cntr=.3,.1

Type RM Length L Ch R = 1 ,2421.262,1130.96,1064.57,987.67
XS GIS Cut Line= 6
     3228161.731    13793245.116     3227873.684    13793237.334
     3227689.291    13793228.719     3227525.219    13793215.967
     3227046.907    13793194.037     3225125.359    13793114.487
#Sta/Elev= 30
  4454.4    6.78 4531.19     7.3 4548.09    9.76 4606.38    6.88 4672.39    2.68
 4761.24    6.89 4946.86     6.7 4964.18    1.13 5026.36    1.19 5043.15    2.71
 5053.14    7.06 5074.84    6.71 5102.24   10.69 5157.49   11.84 5312.46    9.64
 5342.49    8.22 5366.27    3.92 5567.73     4.1 5612.77   11.51 5642.79    7.59
  6058.5    7.55 6093.18   10.11 6153.23   10.63  6217.6     8.1 6358.14    9.94
  6612.5     9.1 7354.26    7.05 7411.03   10.44 7474.36   10.15 7493.98    7.94
#Mann= 6 ,-1 , 0
  4454.4     .07       0 4606.38     .12       0 4946.86    .035       0
 5053.14     .15       0 5366.27     .12       0  6612.5     .15       0
#Block Obstruct= 4 ,-1
 4398.71 4547.16    9.74  4556.1 4879.46     7.3 5168.06    7400      10
 7410.89 7499.09   10.42
Bank Sta=4946.86,5053.14
XS Rating Curve= 0
Exp/Cntr=.3,.1

Type RM Length L Ch R = 1 ,1356.696,23.9,20.68,20.49
XS GIS Cut Line= 6
     3228378.887    13792052.036     3227966.229    13792159.651
     3227866.352     13792171.62     3227425.637    13792213.645
     3226551.786    13792244.696     3225390.529    13792191.508
#Sta/Elev= 30
  4413.7     6.3 4454.15    5.22 4499.75    6.11 4531.43    10.1 4539.12   10.04
 4564.03    7.66 4593.44    4.41 4600.79     4.3 4631.82    4.99 4646.38    6.51
 4655.44    6.31 4666.11    4.82 4699.15    6.17 4779.46    6.44 4801.98     7.6
 4896.06    6.86 4945.83    5.31 4965.16    1.66 5039.83     1.6 5054.17    6.81
 5087.02    7.62 6093.01    6.99 6444.69    7.73 6475.75     6.6 6514.17     8.2
 6603.83    7.47    6660    8.68 6716.13    7.92 6925.29    7.43 7420.36    8.18
#Mann= 4 ,-1 , 0
  4413.7     .07       0 4564.03     .12       0 4896.06    .035       0
 5054.17     .12       0
#Block Obstruct= 4 ,-1
 4385.88 4532.97   10.07 4550.72 4802.12       6    6444    7150     7.7
    5175    6431    7.45
Bank Sta=4896.06,5054.17
XS Rating Curve= 0
Exp/Cntr=.5,.3

Type RM Length L Ch R = 1 ,1336.02 ,43.95,37.56,45.42
XS GIS Cut Line= 6
     3228392.519    13792022.621     3227962.396    13792139.967
     3227607.979    13792178.117     3227424.436    13792193.675
     3226551.888    13792224.679     3225391.444    13792171.529
#Sta/Elev= 30
 4401.78    6.67 4449.47    5.21 4495.35    5.99  4532.5   10.14 4552.85    8.28
 4596.19    4.02 4622.72    3.61 4647.15    4.74 4658.38    6.18 4673.93    4.52
 4826.82     8.8 4874.28    7.95 4905.46    8.27    4934    6.86 4965.16    1.66
 5039.83     1.6 5054.17    6.81 5087.02    7.62 5214.36    8.06 5630.73    6.95
 5695.76    7.98 5723.81    7.41 5926.73    8.35 6046.69    7.18 6429.19    7.44
 6475.94    6.71 6626.94    8.62 6711.93    7.49 6880.33    7.37 7423.11    8.23
#Mann= 4 ,-1 , 0
 4401.78     .07       0 4552.85     .12       0    4934    .035       0
 5054.17     .12       0
#XS Ineff= 2 , 0
       0    4940     8.1    5060       0     8.1
Permanent Ineff=
       F       F
#Block Obstruct= 3 ,-1
  4383.3 4532.83   10.14 4532.83 4825.59       7    5522    7458     7.6
Bank Sta=4934,5054.17
XS Rating Curve= 0
Exp/Cntr=.5,.3

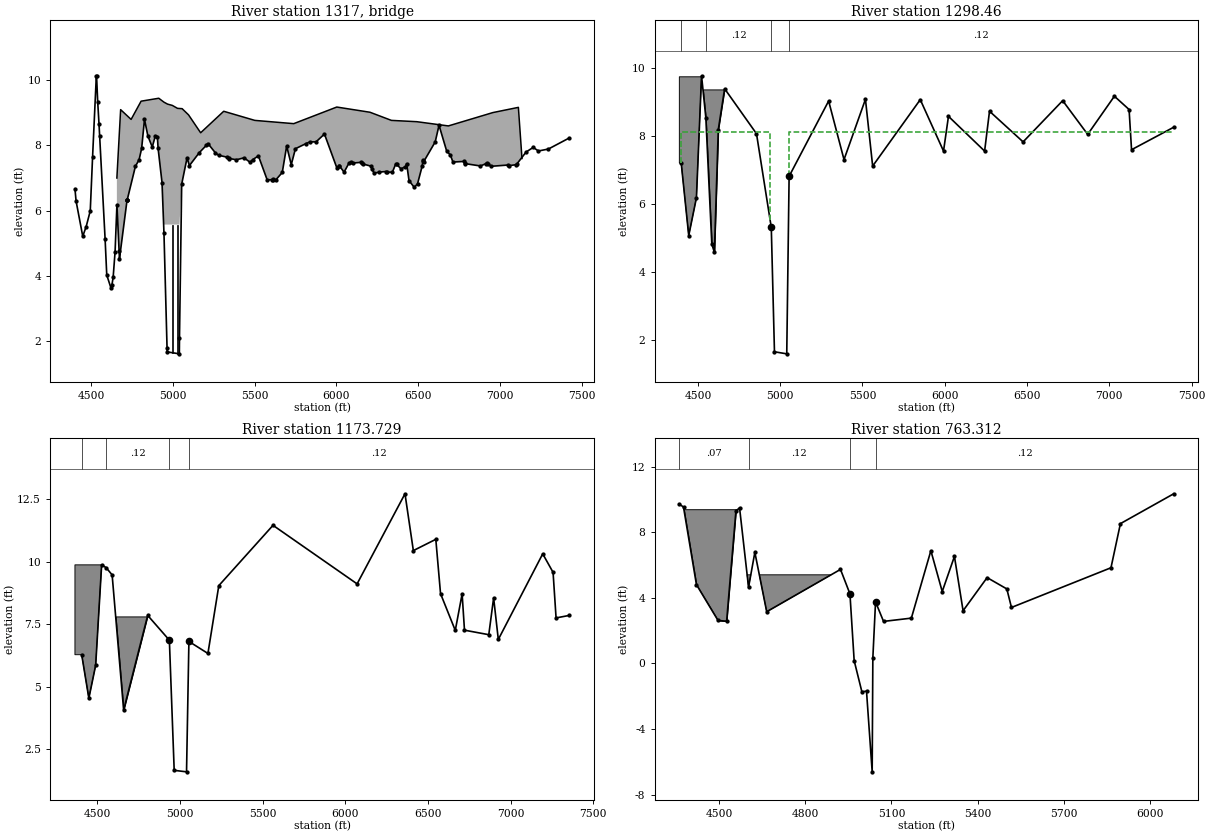
Type RM Length L Ch R = 3 ,1317    ,,,
BEGIN DESCRIPTION:
RAILROAD BRIDGE
END DESCRIPTION:
Bridge Culvert--1,0,-1,-1, 0
Deck Dist Width WeirC Skew NumUp NumDn MinLoCord MaxHiCord MaxSubmerge Is_Ogee
12,19,2.6,0, 23, 23, , , .95, 0, 0,0,,
    4658    4681    4745    4806    4914 4945.77 4967.77 4996.97 5028.57 5056.83
    5096    5170    5311    5501    5739    6002    6205    6336    6491    6684
    6956    7112    7134
       7     9.1     8.8    9.36    9.45    9.33    9.27    9.23    9.14    9.13
    8.94    8.39    9.05    8.77    8.67    9.18    9.02    8.77    8.73     8.6
    9.01    9.17     7.6
                                    5.57    5.57    5.57    5.57    5.57    5.57
    5.57    5.57
                        
    4658    4681    4745    4806    4914 4945.77 4967.77 4996.97 5028.57 5056.83
    5096    5170    5311    5501    5739    6002    6205    6336    6491    6684
    6956    7112    7134
       7     9.1     8.8    9.36    9.45    9.33    9.27    9.23    9.14    9.13
    8.94    8.39    9.05    8.77    8.67    9.18    9.02    8.77    8.73     8.6
    9.01    9.17     7.6
                                    5.57    5.57    5.57    5.57    5.57    5.57
    5.57    5.57
                        
Pier Skew, UpSta & Num, DnSta & Num=  ,4997, 4 ,4997, 4 , 3 , 3 , 0 ,,
       2       2     2.5     2.5
       0    3.06   3.061   5.565
       2       2     2.5     2.5
       0    3.06   3.061   5.565
Pier Skew, UpSta & Num, DnSta & Num=  ,5029, 4 ,5029, 4 , 3 , 3 , 0 ,,
       2       2     2.5     2.5
       0    3.06    3.06    5.57
       2       2     2.5     2.5
       0    3.06    3.06    5.57
BR Coef=-1 , 1 , 0 ,1.25, 0 ,,,.8,-1,2,0,
WSPro=,,,, 1 ,,,, 0 ,,,, 0 ,,,,-1 ,-1 ,-1 , 0 , 0 , 0 , 0 , 0
BR U #Sta/Elev= 119
 4401.78    6.67 4408.78    6.29 4449.47    5.21 4470.52    5.51 4495.35    5.99
 4509.48    7.64  4532.5   10.14 4533.99   10.13 4540.74    9.35 4548.98    8.65
 4552.85    8.28 4586.07    5.13 4596.19    4.02 4622.72    3.61 4627.28     3.7
 4635.28    3.95 4647.15    4.74 4658.38    6.18 4671.58    4.76 4673.93    4.52
 4719.95    6.31 4720.44    6.32 4720.81    6.32 4721.32    6.33 4771.39    7.36
 4793.73    7.56 4809.47    7.91 4826.82     8.8 4847.62    8.29 4874.28    7.95
 4893.51     8.3 4905.46    8.27    4910    7.91    4934    6.86 4945.83    5.31
 4964.67    1.79 4965.16    1.66 5039.83     1.6 5040.69     2.1 5054.17    6.81
 5087.02    7.62 5101.14    7.38 5161.88    7.78 5204.15       8 5214.36    8.06
 5260.63    7.77 5279.33     7.7 5331.37    7.64 5342.66    7.57 5345.81     7.6
 5388.35    7.56 5435.11    7.62 5472.98    7.48 5487.34    7.56 5523.07    7.68
 5576.88    6.94  5609.1    6.95  5611.1    6.95 5613.37    6.97 5630.73    6.95
 5668.91    7.17 5695.76    7.98 5723.81    7.41 5749.41     7.9 5814.96    8.06
 5838.95    8.11 5875.33    8.11 5926.73    8.35 6001.83    7.32 6017.45    7.37
 6018.22    7.37 6046.69    7.18 6076.77    7.46 6089.37    7.49 6100.67    7.46
 6147.58    7.48 6153.31    7.45 6163.63    7.43 6213.34    7.36 6216.62    7.27
 6230.13    7.15 6261.45    7.18 6301.33     7.2 6311.69    7.18 6341.98    7.18
 6361.39    7.42 6367.85    7.42 6394.62    7.28 6422.05    7.35 6429.19    7.44
 6443.51    6.92 6475.94    6.71 6496.04    6.83 6524.86    7.38  6528.1    7.54
 6529.45    7.51  6533.1     7.5 6603.73    8.11 6626.94    8.62 6674.09    7.82
 6696.19    7.71 6711.93    7.49  6781.2    7.51 6783.92    7.47 6788.72    7.44
 6880.33    7.37 6913.07    7.44 6919.06    7.45 6924.45    7.44 6946.23    7.36
 7051.33     7.4 7055.48    7.38  7098.8    7.41 7101.04    7.42 7159.31     7.8
 7202.72    7.94 7234.39    7.83 7295.23    7.89 7423.11    8.23
BR U #Mann= 4
 4401.78     .07 4552.85     .12    4934    .023 5054.17     .12
BR D #Sta/Elev= 128
 4398.55     7.2 4402.02    7.15 4414.09    6.88 4419.75    6.56 4444.27    5.07
 4463.82    5.77 4491.01    6.18 4497.35    7.06 4518.86    9.52 4522.17    9.76
 4536.99    9.58 4538.16     9.5 4542.41    9.11 4548.16    8.53  4584.5    4.82
 4599.59    4.59 4600.08    4.58 4623.91    8.18 4631.25     8.3 4644.32    8.81
 4662.41    9.38 4665.99    9.37 4684.72     8.5 4700.17    8.69 4715.92    8.11
 4752.11    8.21 4774.77     7.9 4812.36    8.38 4830.67    7.45  4839.4    7.65
 4849.39    8.15    4856    8.06    4910    6.86 4945.83    5.31 4964.67    1.79
 4965.16    1.66 5039.83     1.6 5040.69     2.1 5054.17    6.81 5087.02    7.62
 5101.14    7.38 5124.21     7.3 5147.17    7.99 5163.46    7.94 5182.88    8.43
 5256.75    8.77 5294.31    9.02 5315.77    9.01 5331.99    7.74 5345.34    7.76
 5359.85    7.45 5362.42    7.37 5363.63    7.37 5387.76     7.3 5396.12    7.36
 5453.22     7.5 5467.21    7.49 5474.71    7.55 5517.97    9.07 5523.59    8.04
 5544.83    7.38 5561.77    7.11 5574.66    7.35 5582.25    7.39  5647.9    8.54
 5662.26    8.69  5673.7     8.4 5680.92    8.36 5755.18    8.41 5772.85    8.06
  5792.2    8.43 5822.01    8.13 5838.29     8.2 5851.07    9.06 5875.48    8.22
    5904    8.05 5947.34    8.58 5990.94    7.56 5992.35    7.55 6011.13    8.17
 6022.36    8.57 6050.53    8.06  6051.9    7.99 6053.35    7.99 6096.39    7.87
 6099.44    7.88 6166.96    7.56 6170.55    7.55 6178.25    7.56 6242.04    7.55
 6253.06     7.8 6265.81    8.44 6271.76    8.72 6282.64     8.7 6294.79    7.88
 6325.27     7.9 6346.21    8.21  6373.2    8.34 6397.56    8.24  6413.1    8.34
 6451.86    8.25 6475.92    7.82 6503.41    7.85 6522.51    7.92 6532.69     8.1
 6548.82    8.49 6592.38    8.17 6634.62    7.96 6679.77    8.32    6710    8.98
 6712.86    8.97 6716.32    9.03 6748.73    8.82 6774.31    8.41 6802.95    8.29
 6868.28    8.04 6927.69    8.31  7021.7    8.85 7030.52    9.16 7052.25    8.85
 7092.97    8.65 7119.82    8.77 7134.75    7.59 7163.29    7.78 7220.19    7.97
 7238.37     7.9 7273.33    7.93 7390.83    8.25
BR D #Mann= 4
 4398.55     .07 4548.16     .12 4945.83    .023 5054.17     .12
BC Design=,, 0 ,, 0 ,,,,,,

Type RM Length L Ch R = 1 ,1298.46 ,124.22,124.73,113.39
XS GIS Cut Line= 6
     3228398.975    13791977.423     3227955.783    13792102.035
     3227752.796    13792125.394     3227421.034    13792152.032
     3226551.588    13792172.298     3225427.647    13792122.894
#Sta/Elev= 30
 4398.55     7.2 4444.27    5.07 4491.01    6.18 4522.17    9.76 4548.16    8.53
  4584.5    4.82 4600.08    4.58 4623.91    8.18 4662.41    9.38    4856    8.06
 4945.83    5.31 4965.16    1.66 5039.83     1.6 5054.17    6.81 5294.31    9.02
 5387.76     7.3 5517.97    9.07 5561.77    7.11 5851.07    9.06 5992.35    7.55
 6022.36    8.57 6242.04    7.55 6271.76    8.72 6475.92    7.82 6716.32    9.03
 6868.28    8.04 7030.52    9.16 7119.82    8.77 7134.75    7.59 7390.83    8.25
#Mann= 4 ,-1 , 0
 4398.55     .07       0 4548.16     .12       0 4945.83    .035       0
 5054.17     .12       0
#XS Ineff= 2 , 0
       0    4940     8.1 5054.17       0     8.1
Permanent Ineff=
       F       F
#Block Obstruct= 3 ,-1
 4387.21 4523.45    9.73  4525.9 4664.29    9.36
Bank Sta=4945.83,5054.17
XS Rating Curve= 0
Exp/Cntr=.5,.3

Type RM Length L Ch R = 1 ,1173.729,334.48,410.42,505.8
XS GIS Cut Line= 6
     3228411.889    13791865.504     3227932.687    13791987.418
     3227740.507     13792005.99     3227415.133    13792038.908
     3226552.684    13792069.553     3225481.991    13792021.616
#Sta/Elev= 30
 4405.71    6.28 4448.97    4.54 4490.24    5.86 4526.36    9.87 4553.18    9.76
 4589.76    9.47 4659.35    4.07 4804.96    7.85    4936    6.86 4965.16    1.66
 5039.83     1.6 5054.17    6.81 5169.18    6.33 5235.06    9.04 5562.94   11.45
 6071.54    9.11 6361.23   12.71 6411.77   10.44 6547.63   10.89 6576.25    8.72
 6665.41    7.25  6706.8    8.71 6721.09    7.26 6868.07    7.08 6897.33    8.55
 6925.72    6.89 7194.35   10.31 7256.97    9.57 7275.08    7.75 7355.05    7.85
#Mann= 4 ,-1 , 0
 4405.71     .07       0 4553.18     .12       0    4936    .035       0
 5054.17     .12       0
#Block Obstruct= 3 ,-1
 4364.85 4528.85    9.87 4595.19 4806.18    7.81
Bank Sta=4936,5054.17
XS Rating Curve= 0
Exp/Cntr=.3,.1

Type RM Length L Ch R = 1 ,763.312 ,578.7,763.31,649.39
XS GIS Cut Line= 5
     3228549.447    13791626.741     3227956.644     13791595.01
     3227868.083    13791584.729     3227628.178    13791564.732
     3226830.927     13791520.44
#Sta/Elev= 30
 4361.13    9.71 4375.63    9.53  4420.7     4.8  4495.8    2.62 4525.85    2.57
 4558.31     9.3 4570.91    9.48 4602.21    4.64 4624.15    6.77 4665.45    3.15
 4922.49    5.73 4955.42    4.24 4970.09     .17 4996.98   -1.73  5013.1   -1.69
 5032.86   -6.61 5035.18     .33 5044.58    3.75 5072.46    2.56 5169.36    2.76
 5237.33    6.87 5276.88    4.38 5319.38    6.52  5349.5    3.21 5433.24    5.23
  5501.9    4.54 5518.03    3.41 5864.68    5.83 5897.57    8.52 6083.15   10.34
#Mann= 4 ,-1 , 0
 4361.13     .07       0 4602.21     .12       0 4955.42    .035       0
 5044.58     .12       0
#Block Obstruct= 2 ,-1
 4338.26  4567.1     9.4    4590    4910     5.4
Bank Sta=4955.42,5044.58
XS Rating Curve= 0
Exp/Cntr=.3,.1

Chan Stop Cuts=-1